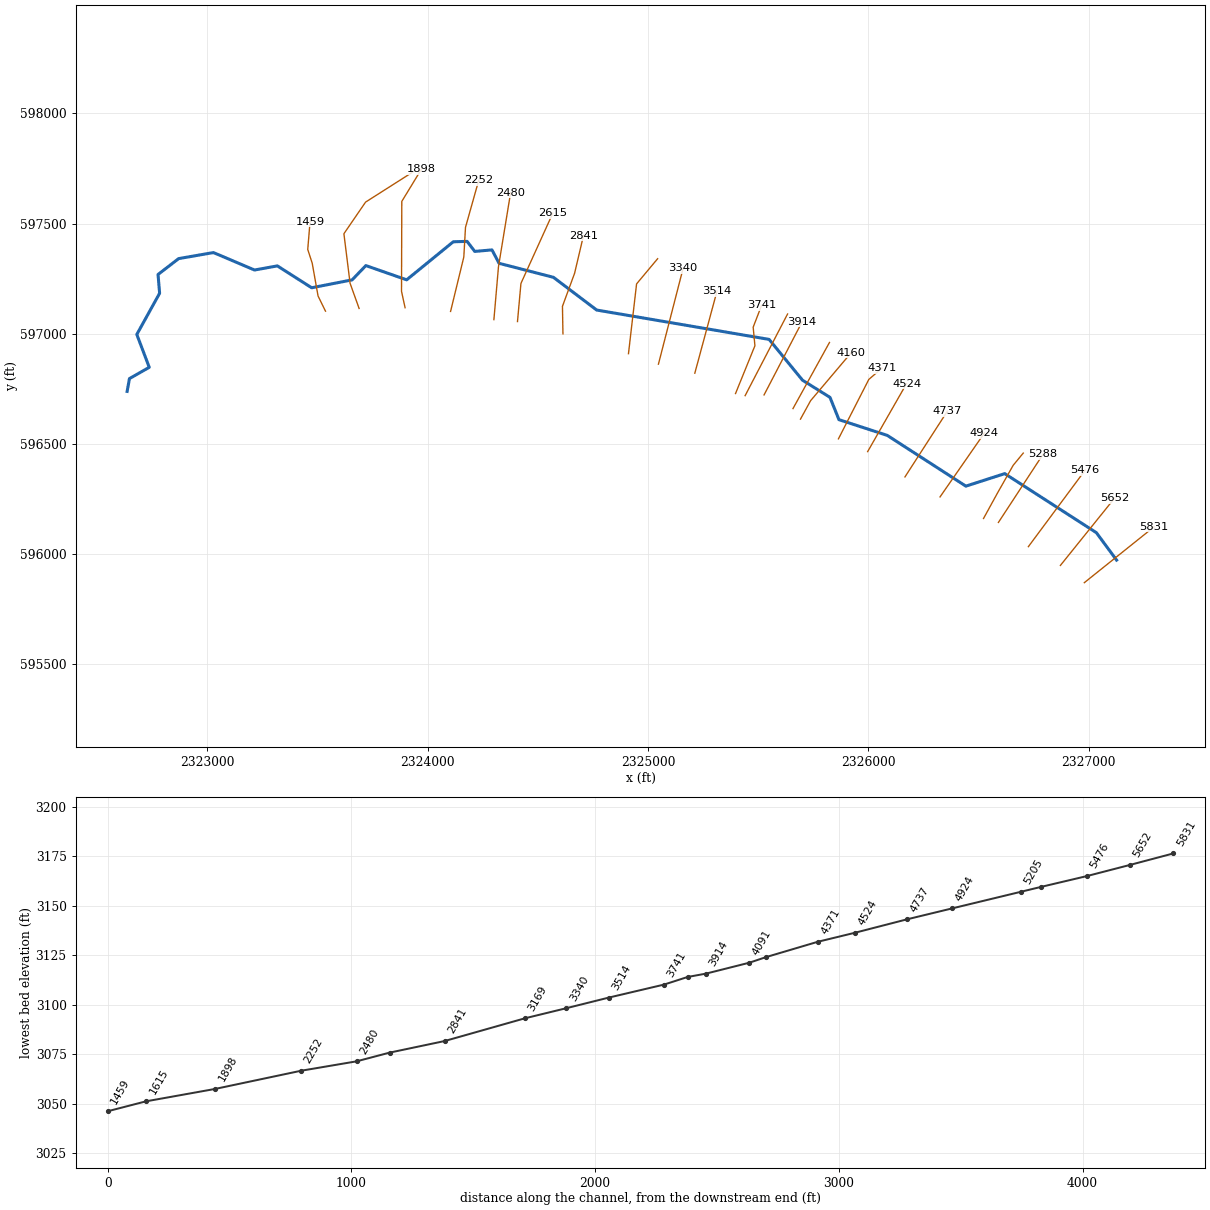
--- CLBHSERN.prj (project) ---

Proj Title=CLBHSERN
Current Plan=p01
Default Exp/Contr=0,0
English Units
Geom File=g01
Flow File=f01
Plan File=p01
Background Map Layer=Inundation Boundary (01pct Value_0)
Background Map Layer=LTTLRV1_River
Background Map Layer=Inundation Boundary (01pct Value_0)
BEGIN DESCRIPTION:
----------MODEL BY WOOD PLC 2021----------
Stream Name: Clubhouse Run
Flood Zone: Enhanced Approximate
Pocahontas County, WV
HEC-RAS Version: RAS 6.1
Vertical Datum: NAVD88
Projection: NAD 1983 StatePlane West Virginia S FIPS 4702 (US Feet)
Terrain: 1-meter LIDAR (FEMA Region III 3DEP collected 2016-2018)
Land Use: 2019 NLCD
Hydrologic Method:
WV SIR2010-5033 regression equations
END DESCRIPTION:
DSS File=dss
DSS Export Rating Curves= 0
DSS Export Rating Curve Sorted= 0
DSS Export Volume Flow Curves= 0
DXF OffsetX= 0
DXF OffsetY= 0
DXF ScaleX= 0
DXF ScaleY= 0

--- CLBHSERN.p01 (plan) ---

Plan Title=Floodplain
Program Version=6.10
Short Identifier=Floodplain
Geom File=g01
Flow File=f01
Subcritical Flow
K Sum by GR= 0
Std Step Tol= 0.01
Critical Tol= 0.01
Num of Std Step Trials= 20
Max Error Tol= 0.3
Flow Tol Ratio= 0.001
Split Flow NTrial= 30
Split Flow Tol= 0.02
Split Flow Ratio= 0.02
Log Output Level= 0
Friction Slope Method= 1
Unsteady Friction Slope Method= 2
Unsteady Bridges Friction Slope Method= 1
Parabolic Critical Depth
Global Vel Dist= 0 , 0 , 0
Global Log Level= 0
CheckData=True
Encroach Param=-1 ,0,0, 0
Computation Interval=0.1SEC
Output Interval=1SEC
Instantaneous Interval=Max Profile
Mapping Interval=1HOUR
Computation Time Step Use Courant=        0
Computation Time Step Use Time Series=    0
Computation Time Step Count To Double=0
Computation Time Step Max Doubling=0
Computation Time Step Max Halving=0
Computation Time Step Residence Courant=0
Run HTab= 0
Run UNet= 0
Run Sediment= 0
Run PostProcess= 0
Run WQNet= 0
Run RASMapper=-1
UNET Theta= 0
UNET Theta Warmup= 0
UNET ZTol= 0
UNET ZSATol= 0
UNET MxIter= 0
UNET Max Iter WO Improvement= 0
UNET MaxInSteps= 0
UNET DtIC= 0
UNET DtMin= 0
UNET MaxCRTS= 0
UNET WFStab= 0
UNET SFStab= 0
UNET WFX= 1
UNET SFX= 1
UNET Gravity=32.174
UNET 1D Methodology=Finite Difference
UNET DSS MLevel= 1
UNET Pardiso=0
UNET DZMax Abort= 0
UNET Use Existing IB Tables= 0
UNET Froude Reduction=False
UNET Froude Limit= 0
UNET Froude Power= 0
UNET D1 Cores= 0
UNET WindReference=Eulerian
UNET WindDragFormulation=Hsu (1988)
UNET D2 Coriolis=0
UNET D2 Cores= 0
UNET D2 Theta= 1
UNET D2 Theta Warmup= 1
UNET D2 Z Tol= 0.01
UNET D2 Volume Tol= 0.01
UNET D2 Max Iterations= 20
UNET D2 Equation= 0
UNET D2 RampUpFraction=0.1
UNET D2 TimeSlices= 1
UNET D2 Turbulence Formulation=Non-Conservative (original)
UNET D2 Eddy Viscosity=0.3
UNET D2 Transverse Eddy Viscosity=0.1
UNET D2 Smagorinsky Mixing=0
UNET D2 BCVolumeCheck=0
UNET D2 Cores=0
UNET D2 SolverType=PARDISO (Direct)
UNET D2 Minimum Iterations= 2147483647
UNET D2 Maximum Iterations= 2147483647
UNET D2 Restart Number= 10
UNET D2 Relaxation Coeff=1.3
UNET D2 SOR Precondition Iterations= 10
UNET D2 ILUT Maximum Fill= 8
UNET D2 ILUT Tolerance=1E-08
UNET D1D2 MaxIter= 0
UNET D1D2 ZTol=0.01
UNET D1D2 QTol=0.1
UNET D1D2 MinQTol=1
DSS File=dss
Write IC File= 0
Write IC File at Fixed DateTime=0
Write IC File at Sim End=0
Echo Input=False
Echo Parameters=False
Echo Output=False
Write Detailed= 0
HDF Write Warmup=0
HDF Write Time Slices=0
HDF Flush=0
HDF Compression= 1
HDF Chunk Size= 1
HDF Spatial Parts= 1
HDF Use Max Rows=0
HDF Fixed Rows= 1
Calibration Method= 0
Calibration Iterations= 20
Calibration Max Change=0.05
Calibration Tolerance=0.2
Calibration Maximum=1.5
Calibration Minimum=0.5
Calibration Optimization Method= 1
WQ AD Non Conservative
WQ ULTIMATE=-1
WQ Max Comp Step=1HOUR
WQ Output Interval=15MIN
WQ Output Selected Increments= 0
WQ Output face flow=0
WQ Output face velocity=0
WQ Output face area=0
WQ Output face dispersion=0
WQ Output cell volume=0
WQ Output cell surface area=0
WQ Output cell continuity=0
WQ Output cumulative cell continuity=0
WQ Output face conc=0
WQ Output face dconc_dx=0
WQ Output face courant=0
WQ Output face peclet=0
WQ Output face adv mass=0
WQ Output face disp mass=0
WQ Output cell mass=0
WQ Output cell source sink temp=0
WQ Output nsm pathways=0
WQ Output nsm derived pathways=0
WQ Create Restart=0
WQ Fixed Restart=0
WQ System Summary=0
WQ Write To DSS=0
Sorting and Armoring Iterations= 10
XS Update Threshold= 0.02
Bed Roughness Predictor= 0
Hydraulics Update Threshold= 0.02
Energy Slope Method= 1
Volume Change Method= 1
Sediment Retention Method= 0
Sediment TS Multiplier= 1
Warm Up Method= 0
XS Weighting Method= 0
Number of US Weighted Cross Sections= 1
Number of DS Weighted Cross Sections= 1
Upstream XS Weight=0
Main XS Weight=1
Downstream XS Weight=0
Number of DS XS's Weighted with US Boundary= 1
Upstream Boundary Weight= 1
Weight of XSs Associated with US Boundary= 0
Number of US XS's Weighted with DS Boundary= 1
Downstream Boundary Weight= 0.5
Weight of XSs Associated with DS Boundary= 0.5
Percentile Method= 0
Sediment Output Level= 3
Mass or Volume Output= 0
Output Increment Type= 1
Profile and TS Output Increment= 1
Transport Output Increment 1
XS Output Flag= 0
XS Output Increment= 10
Read HDF5 Sediment Hotstart= 0
Sediment Hotstart Type= 0
Write Gradation File= 0
Read Gradation Hotstart= 0
Write HDF5 File= 1
Write Binary Output= 1
Write DSS Sediment File= 0
DSS Sediment Output Type= 1
SV Curve= 0
Specific Gage Flag= 0
Subcell Erosion Methods= 0
Subcell Deposition Methods= 0
Advection Scheme= 1
Matrix Solver= 0
Implicit Weighting Factor= 1
Maximum Outer Loop Convergence Iterations= 5
Convergence Maximum Absolute= 0.001
Convergence RMSE= 0.0001
Grain Fractions Max Abs Error= 0.001
Max Subgrid Regions= 1
Max Subgrid Length Scale= 3.402823E+38
Initial Layer Thickness= 3.402823E+38
Min Layer Thickness= 3.402823E+38
Max Layer Thickness= 3.402823E+38
Number of Layers= 5

--- CLBHSERN.f01 (steady flow) ---

Flow Title=Flow
Program Version=6.10
Number of Profiles= 6
Profile Names=01pct,10pct,04pct,02pct,0_2pct,01plus
River Rch & RM=CLBHSERN,Main,5831
     723     386     511     613    1010    1070
Boundary for River Rch & Prof#=CLBHSERN,Main            , 1
Up Type= 0
Dn Type= 3
Dn Slope=0.00826
Boundary for River Rch & Prof#=CLBHSERN,Main            , 2
Up Type= 0
Dn Type= 3
Dn Slope=0.00826
Boundary for River Rch & Prof#=CLBHSERN,Main            , 3
Up Type= 0
Dn Type= 3
Dn Slope=0.00826
Boundary for River Rch & Prof#=CLBHSERN,Main            , 4
Up Type= 0
Dn Type= 3
Dn Slope=0.00826
Boundary for River Rch & Prof#=CLBHSERN,Main            , 5
Up Type= 0
Dn Type= 3
Dn Slope=0.00826
Boundary for River Rch & Prof#=CLBHSERN,Main            , 6
Up Type= 0
Dn Type= 3
Dn Slope=0.00826
DSS Import GetInterval= 0
DSS Import GetPeak= 0
DSS Import FillOption= 0

--- CLBHSERN.g01 (geometry) ---

Geom Title=Geometry
Program Version=6.10

River Reach=CLBHSERN        ,Main
Reach XY= 30
2327126.64298294595972.6500402032327034.86800005596097.011999995
     2326619.075596365.024000004     2326442.611596308.246999994
2326085.68900003596538.6530000122325866.46661252596610.043600296
2325825.90100001596711.2280000152325701.20299067596789.035450915
2325549.56300001      596974.2282324766.98800001597107.513999999
2324570.62635321 597256.034018722324323.92396844597319.604504391
2324291.73615592597380.5088042892324213.70582978597373.577176332
2324178.65800002597419.2099303912324116.06889885597417.345455716
2323904.47700001 597244.689000012323719.37559558597309.312171879
2323656.98102038597244.4707505882323473.37000003597208.540999994
2323317.62532209597307.9106267682323214.03597416597289.183376038
2323027.58100003597368.3560000362322869.57231357597340.910237903
2322776.11500001597268.8890000132322783.22809245597183.690959172
2322679.78900005596996.7750000062322736.13801215 596847.44625306
2322646.32700002596796.349000007 2322635.8379063596738.297070637

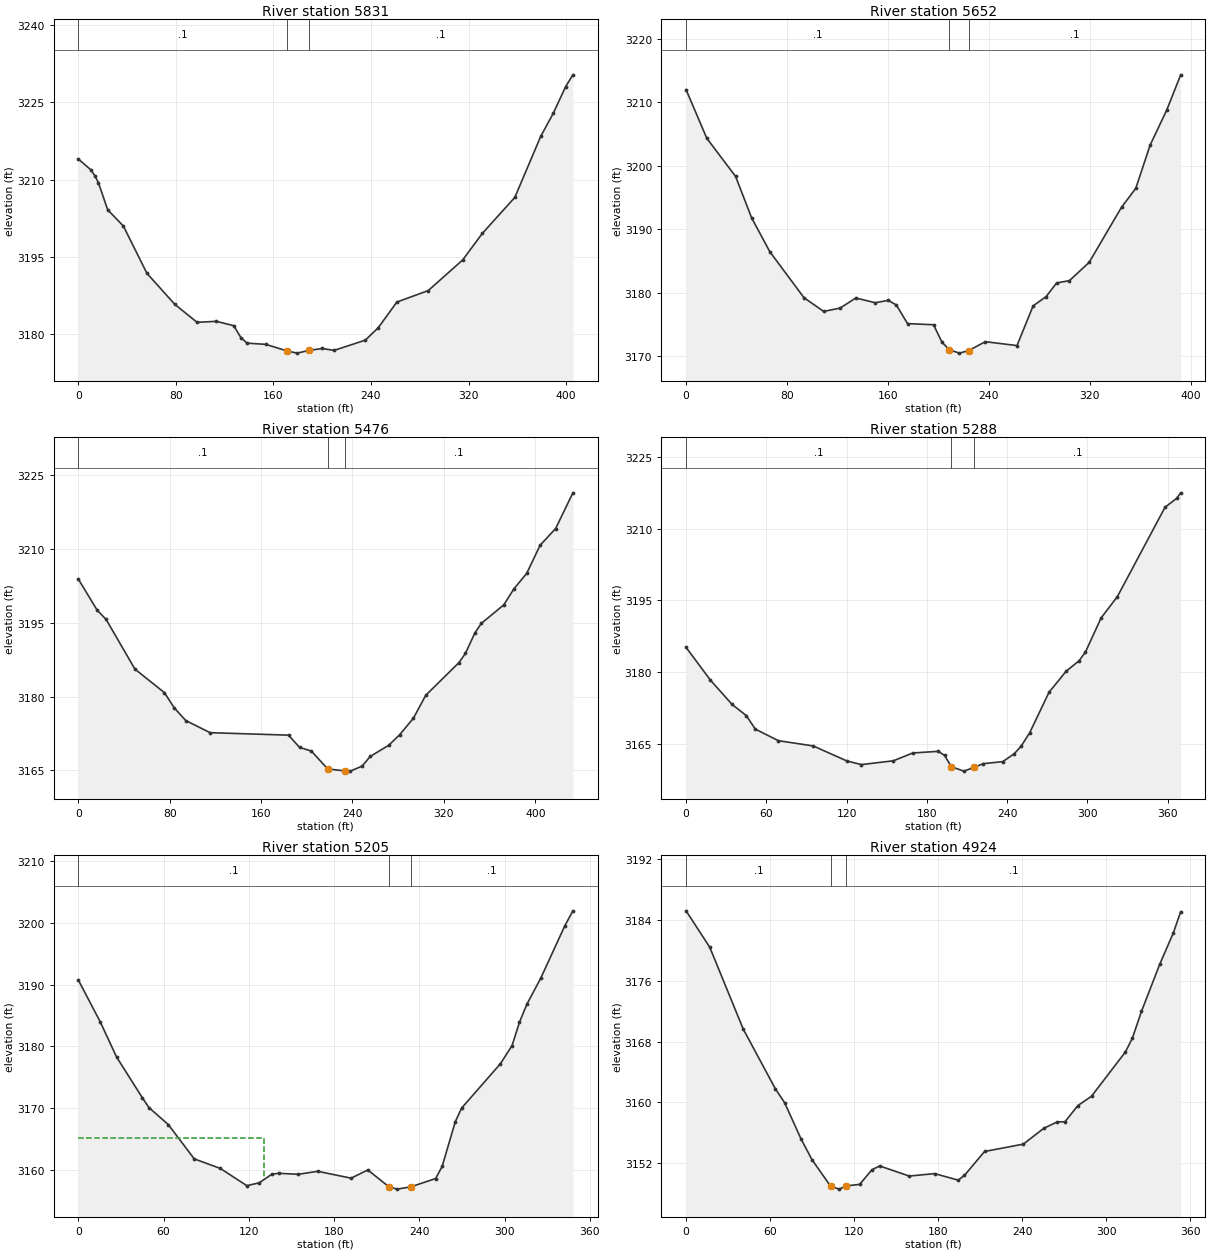
Type RM Length L Ch R = 1 ,5831    ,177.2,179.7,182.1
XS GIS Cut Line= 2
2326980.09508614595870.0894893582327296.75374506596123.517893253
#Sta/Elev= 30
       0    3214    10.3 3211.89    13.6 3210.73    16.5  3209.4    24.1 3204.15
      37 3200.97    56.3 3191.81    79.1  3185.8    97.4  3182.3   113.2 3182.49
   127.5 3181.64   133.3 3179.35   138.4 3178.26   153.8 3178.02   171.4 3176.73
   179.4 3176.32   189.23176.841   199.9 3177.22   209.8 3176.85   235.4 3178.84
     246 3181.25   261.2 3186.22     287 3188.46   315.3 3194.42   331.4 3199.57
     358 3206.54   379.2 3218.37   389.5 3222.85   399.7 3228.05   405.6 3230.32
#Mann= 3 ,-1,0
       0      .1       0   171.4    .045       0   189.2      .1       0
Bank Sta=171.4,189.2
XS Rating Curve= 0 ,0
Exp/Cntr=0.3,0.1

Type RM Length L Ch R = 1 ,5652    ,175.7,176.1,176.8
XS GIS Cut Line= 2
2326871.55431447 595948.389003552327117.57224622596253.838233415
#Sta/Elev= 30
       0 3211.96    16.4 3204.31    39.3 3198.28      52 3191.76    66.4 3186.44
    93.5 3179.19   109.1 3177.03   122.1 3177.55   134.6 3179.14     150  3178.4
   160.4 3178.77   166.8 3178.03   175.6 3175.11   196.2 3174.93     203 3172.16
   208.7    3171   216.7 3170.46   224.2 3170.87   237.3 3172.26   262.4 3171.65
   275.2  3177.9   285.5 3179.36   293.8 3181.51     304 3181.88   319.6 3184.75
   345.3 3193.44   356.6 3196.41     368 3203.24   381.1 3208.72   392.2 3214.29
#Mann= 3 ,-1,0
       0      .1       0   208.7    .045       0   224.2      .1       0
Bank Sta=208.7,224.2
XS Rating Curve= 0 ,0
Exp/Cntr(USF)=0,0
Exp/Cntr=0.3,0.1

Type RM Length L Ch R = 1 ,5476    ,186.7,187.7,188.1
XS GIS Cut Line= 2
2326726.28262333596033.6377161212326984.21998566 596381.24861457
#Sta/Elev= 30
       0 3203.88    16.6 3197.52    24.3 3195.69    49.6 3185.57    75.4 3180.79
    83.9 3177.73    94.1 3175.12   115.4 3172.66     184 3172.16   193.7 3169.67
     204 3168.93   218.3 3165.29   233.33164.898   238.1 3164.85   248.5 3165.88
   255.5 3167.83   271.7  3170.1   281.2 3172.22   293.3 3175.59   304.1 3180.25
   333.2  3186.9   338.8 3188.75     347 3192.86   352.7 3194.85   372.4 3198.62
   381.3 3201.88   392.5 3205.03   404.2 3210.73   417.8 3214.13   432.9 3221.38
#Mann= 3 ,-1,0
       0      .1       0   218.3    .045       0   233.3      .1       0
Bank Sta=218.3,233.3
XS Rating Curve= 0 ,0
Exp/Cntr(USF)=0,0
Exp/Cntr=0.3,0.1

Type RM Length L Ch R = 1 ,5288    ,82.1,82.7,83.8
XS GIS Cut Line= 2
2326590.26096741596143.4626086742326792.78209955596452.785929902
#Sta/Elev= 30
       0 3185.22    18.1 3178.42    34.4 3173.31    45.1 3170.97    51.7 3168.17
      69 3165.75    95.1 3164.65   120.3 3161.51   131.1 3160.76     155 3161.56
   169.4 3163.18   188.5 3163.53   193.3 3162.66   198.23160.335   207.6  3159.4
   215.3 3160.18     222 3160.95   236.7 3161.38   245.3 3163.02   250.7  3164.7
   256.9 3167.44   271.3 3175.85   284.1 3180.24   293.7 3182.41   298.5 3184.22
   310.2 3191.35   322.4 3195.81     358 3214.44   366.7 3216.29   369.7 3217.45
#Mann= 3 ,-1,0
       0      .1       0   198.2    .045       0   215.3      .1       0
Bank Sta=198.2,215.3
XS Rating Curve= 0 ,0
Exp/Cntr(USF)=0,0
Exp/Cntr=0.3,0.1

Type RM Length L Ch R = 1 ,5205    ,283.4,280.8,284.9
XS GIS Cut Line= 4
2326522.75392337596161.5988294632326585.22312831596275.453993303
2326657.33273272596402.8136843772326703.00174172596458.218816205
#Sta/Elev= 30
       0 3190.75    15.5 3183.95    26.9 3178.31    45.1 3171.69    49.7 3170.12
    63.4 3167.35    81.6 3161.82    99.9 3160.28   118.6 3157.49   127.3 3157.95
   136.2 3159.34     141 3159.49   154.8 3159.33   168.5 3159.81     192  3158.7
   203.7 3160.03   218.4 3157.34   224.3 3156.93     2343157.301   251.4 3158.64
     256 3160.59   265.2 3167.79   269.7 3170.03     297  3177.2   305.2 3180.14
   310.4  3183.9   315.6 3186.81   325.4 3191.04   342.4 3199.54     348 3201.92
#Mann= 3 ,-1,0
       0      .1       0   218.4    .045       0     234      .1       0
#XS Ineff= 2 , 0
           130.9 3165.24
Permanent Ineff=
       F       F
Bank Sta=218.4,234
XS Rating Curve= 0 ,0
Exp/Cntr(USF)=0,0
Exp/Cntr=0.3,0.1

Type RM Length L Ch R = 1 ,4924    ,187,187.5,187.6
XS GIS Cut Line= 2
2326325.27063034596259.3329081572326526.78419465596549.512440775
#Sta/Elev= 30
       0 3185.19    16.9 3180.41    40.8 3169.65    63.8 3161.77    70.4 3159.95
    82.2 3155.15    89.9 3152.47   103.3 3148.95   109.4 3148.58   114.3 3149.01
     124  3149.2   132.7 3151.12   138.3 3151.63   159.4  3150.3   177.6 3150.62
   194.4 3149.76   198.8 3150.38   213.2 3153.53   240.9  3154.5   255.5 3156.58
     265 3157.41   270.7 3157.45   279.8 3159.56   289.6  3160.8   313.8 3166.62
   318.8 3168.44   325.3 3171.96   338.3 3178.15     348 3182.26   353.3 3185.07
#Mann= 3 ,-1,0
       0      .1       0   103.3    .045       0   114.3      .1       0
Bank Sta=103.3,114.3
XS Rating Curve= 0 ,0
Exp/Cntr(USF)=0,0
Exp/Cntr=0.3,0.1

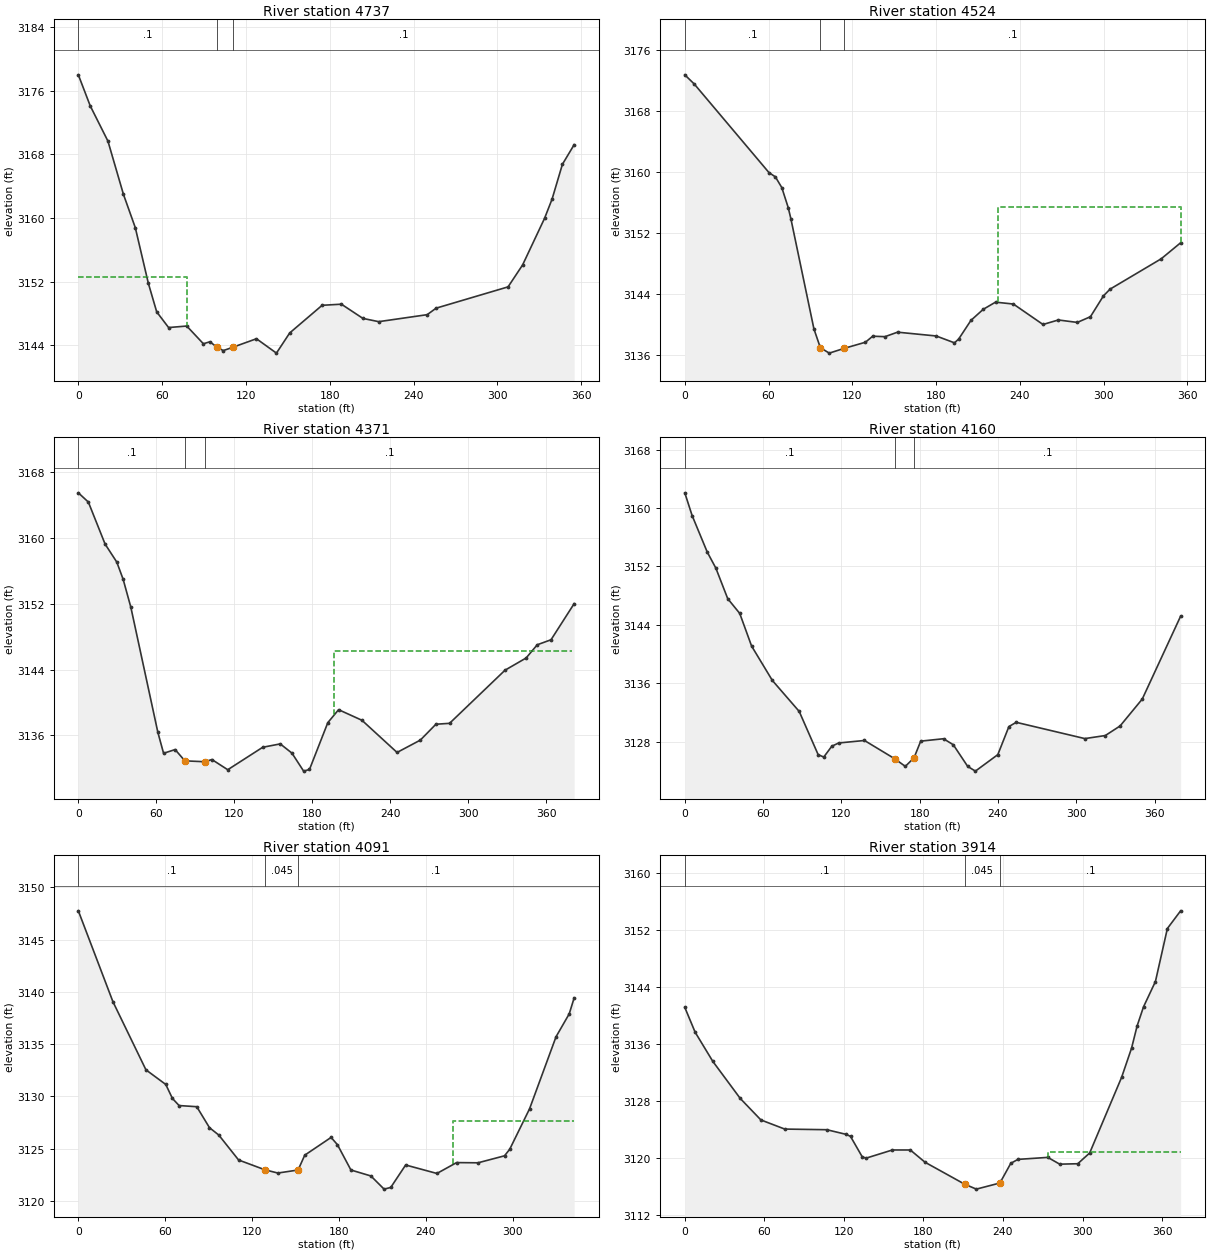
Type RM Length L Ch R = 1 ,4737    ,211.4,212.9,213.2
XS GIS Cut Line= 2
2326166.07491453  596350.01401212326358.52036845596648.254087291
#Sta/Elev= 30
       0 3178.02     8.5 3174.12    21.2 3169.67    32.3 3162.97    40.8 3158.77
    50.1 3151.79    56.1 3148.18    64.6 3146.21    77.6  3146.4    89.5 3144.17
    94.2 3144.42      99 3143.76   103.7 3143.31   110.9 3143.74   110.9 3143.75
   127.5  3144.8   141.8 3142.99   151.3 3145.53   174.5 3149.01   188.3 3149.15
   203.7 3147.36     215 3146.95   249.7 3147.83   256.1 3148.65   307.6 3151.33
     318 3154.09   333.7 3159.95   339.1 3162.38   346.5 3166.76   354.9 3169.23
#Mann= 3 ,-1,0
       0      .1       0      99    .045       0   110.9      .1       0
#XS Ineff= 2 , 0
           77.51 3152.53
Permanent Ineff=
       F       F
Bank Sta=99,110.9
XS Rating Curve= 0 ,0
Exp/Cntr(USF)=0,0
Exp/Cntr=0.3,0.1

Type RM Length L Ch R = 1 ,4524    ,151.3,152.7,152.7
XS GIS Cut Line= 2
 2325996.8035205596464.8767437622326173.12788928596773.192497168
#Sta/Elev= 30
       0 3172.75     6.8 3171.54    60.3 3159.92    64.9 3159.36    69.5 3157.95
    74.1 3155.32      76 3153.86    92.5 3139.41    97.1 3136.94   103.5 3136.23
   114.1 3136.85   129.4 3137.66   134.6 3138.45   143.4 3138.39   152.4 3138.98
   180.1 3138.48   193.2 3137.58   196.2 3138.08     205 3140.53   213.8 3141.98
   222.6 3142.92   235.4 3142.67   256.6 3139.99   267.6 3140.58   281.2 3140.26
   290.6 3141.01   299.9 3143.74   304.6 3144.62   341.3 3148.61   355.2 3150.71
#Mann= 3 ,-1,0
       0      .1       0    97.1    .045       0   114.1      .1       0
#XS Ineff= 2 , 0
                           224.1         3155.35
Permanent Ineff=
       F       F
Bank Sta=97.1,114.1
XS Rating Curve= 0 ,0
Exp/Cntr(USF)=0,0
Exp/Cntr=0.3,0.1

Type RM Length L Ch R = 1 ,4371    ,213.4,211.8,206.6
XS GIS Cut Line= 3
2325864.18095062596522.8115183542326002.06131088596792.507595489
2326061.65155456596843.917389063
#Sta/Elev= 30
       0 3165.49     7.7 3164.37    20.6 3159.26    29.6 3157.07    34.5 3154.97
    40.4 3151.59    61.2 3136.38    65.6 3133.83    74.5 3134.28      82 3132.91
    97.4  3132.8   102.8 3133.07     115 3131.83   141.9 3134.56   155.4 3134.97
   164.4 3133.85   173.4 3131.66   177.9 3131.86     192 3137.55   200.3 3139.13
   218.3 3137.84   245.3 3133.93   263.2 3135.43   275.2 3137.36   285.7 3137.47
   328.4 3143.93   344.6 3145.41   353.2 3147.02   363.8 3147.63   381.6 3152.02
#Mann= 3 ,0,0
       0      .1       0      82    .045       0    97.4      .1       0
#XS Ineff= 1 ,-1
  196.79   380.2 3146.24
Permanent Ineff=
       F
Bank Sta=82,97.4
XS Rating Curve= 0 ,0
Exp/Cntr(USF)=0,0
Exp/Cntr=0.3,0.1

Type RM Length L Ch R = 1 ,4160    ,65.7,68.2,70.3
XS GIS Cut Line= 3
2325691.87980139596612.2964658672325737.92345509596696.164519488
2325921.55204337596913.259234205
#Sta/Elev= 30
       0 3162.09     5.6 3158.98    17.2 3153.97    23.8 3151.77    32.9 3147.58
    42.1 3145.56    51.2 3141.08    67.1 3136.37    87.7 3132.12   102.2  3126.2
   106.5 3125.87   112.7 3127.36     118  3127.8   137.7 3128.14     1613125.623
     169 3124.59   175.7 3125.77   180.8 3128.05   198.3 3128.38   205.8 3127.55
   216.8 3124.59   222.7 3123.94   239.9  3126.2   248.4 3130.05     254 3130.63
   306.6  3128.4   322.3 3128.82   333.6 3130.13   350.6 3133.82     380 3145.18
#Mann= 3 ,-1,0
       0      .1       0     161    .045       0   175.7      .1       0
Bank Sta=161,175.7
XS Rating Curve= 0 ,0
Exp/Cntr(USF)=0,0
Exp/Cntr=0.3,0.1

Type RM Length L Ch R = 1 ,4091    ,175.7,177.4,181.9
XS GIS Cut Line= 2
2325657.90622891596660.280815467 2325823.4222502596960.172191961
#Sta/Elev= 30
       0 3147.76    23.9 3139.06    46.7 3132.54    60.4 3131.14      65  3129.8
    69.6 3129.12    81.8 3129.01    90.6    3127      97  3126.3   110.7 3123.91
   128.9 3122.97   137.8 3122.66   151.8 3122.95   156.4 3124.37   174.6 3126.07
     179 3125.37   188.3 3122.95   202.1 3122.38   211.2 3121.12   215.8 3121.28
   226.1 3123.43   247.7 3122.62   261.3 3123.66   276.1 3123.64   294.4 3124.31
     298 3124.94   311.7 3128.81     330 3135.71   339.1  3137.9   342.5 3139.43
#Mann= 3 ,-1,0
       0      .1       0   128.9    .045       0   151.8      .1       0
#XS Ineff= 2 , 0
                          259.11         3127.61
Permanent Ineff=
       F       F
Bank Sta=128.9,151.8
XS Rating Curve= 0 ,0
Exp/Cntr(USF)=0,0
Exp/Cntr=0.3,0.1

Type RM Length L Ch R = 1 ,3914    ,76.3,76.3,75.4
XS GIS Cut Line= 2
2325526.63048603596722.2921446932325699.30000913597053.999386434
#Sta/Elev= 30
       0  3141.1     7.8 3137.62    21.1 3133.54    41.8 3128.34    57.4 3125.32
    75.4 3124.04   107.1 3123.95   121.9 3123.29     125 3123.01   133.8 3120.16
   136.7 3119.96   156.6 3121.11   170.1 3121.11   181.2 3119.39     2113116.323
   219.9 3115.62   237.7 3116.48   245.9 3119.24   251.3 3119.79   273.8 3120.07
   282.8 3119.12   296.4 3119.18   305.4 3120.69   329.5  3131.3     337 3135.39
   341.2 3138.51     346 3141.17     355 3144.73     364 3152.16     374 3154.64
#Mann= 3 ,-1,0
       0      .1       0     211    .045       0   237.7      .1       0
#XS Ineff= 2 , 0
                          274.18         3120.88
Permanent Ineff=
       F       F
Bank Sta=211,237.7
XS Rating Curve= 0 ,0
Exp/Cntr(USF)=0,0
Exp/Cntr=0.3,0.1

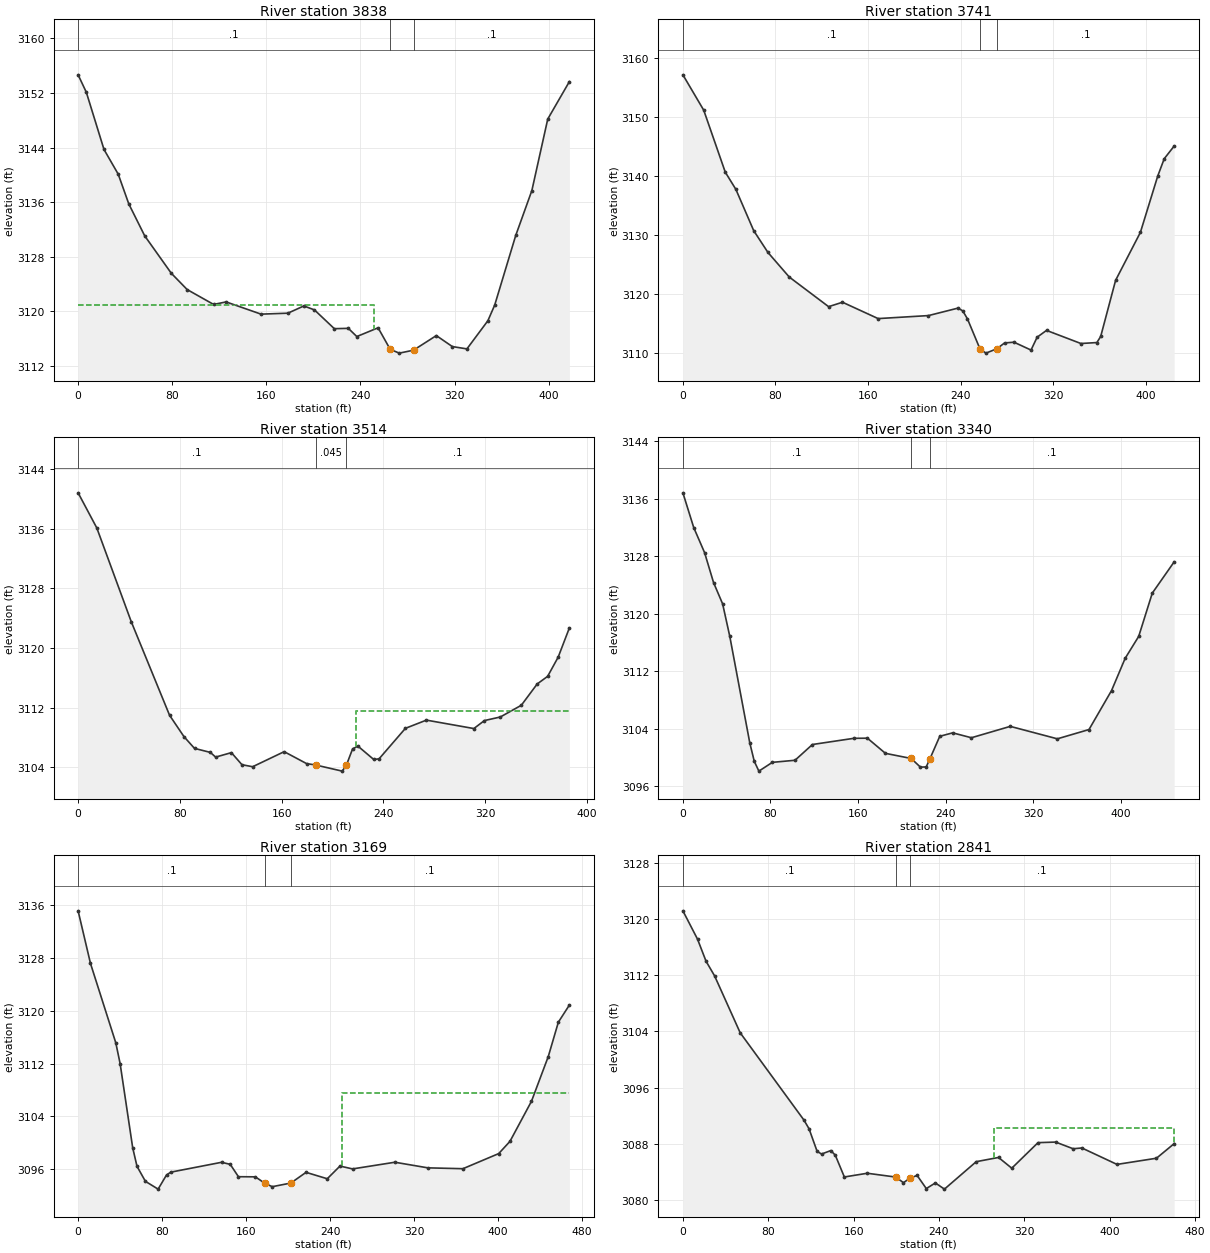
Type RM Length L Ch R = 1 ,3838    ,87.7,96.6,102.2
XS GIS Cut Line= 2
2325440.72758093596718.9403705352325633.28498683 597089.50142492
#Sta/Elev= 30
       0 3154.66       7  3152.1      22 3143.73    34.1 3140.11    43.1 3135.75
    56.6 3131.08    79.2  3125.6    92.7 3123.21   115.2 3121.03   125.8  3121.4
   155.5 3119.61   178.3 3119.75   191.9 3120.81   200.9 3120.23   217.8 3117.48
   229.7 3117.53   236.9 3116.33     255 3117.61   265.3 3114.45     273  3113.9
   285.1 3114.33   304.5 3116.47   318.1 3114.86   330.5 3114.52   348.3 3118.64
   354.1 3120.93     372 3131.14   385.7 3137.71   399.2 3148.18   417.6 3153.67
#Mann= 3 ,-1,0
       0      .1       0   265.3    .045       0   285.1      .1       0
#XS Ineff= 2 , 0
          251.27 3120.99
Permanent Ineff=
       F       F
Bank Sta=265.3,285.1
XS Rating Curve= 0 ,0
Exp/Cntr(USF)=0,0
Exp/Cntr=0.3,0.1

Type RM Length L Ch R = 1 ,3741    ,231.2,227.2,222.5
XS GIS Cut Line= 4
2325397.12834371596728.5400550692325485.16708082596945.512942646
2325477.21519488597029.5757367862325515.27064899597128.406319085
#Sta/Elev= 30
       0  3157.2      18 3151.21    36.6 3140.72    45.8 3137.79    61.2  3130.8
    73.5 3127.11    91.9 3122.95   125.9 3117.93   137.9 3118.68   168.7 3115.91
   212.2 3116.42   237.8 3117.69   241.9  3117.2   245.9 3115.85   256.8 3110.73
   261.9 3110.06   271.33110.801     278 3111.79   286.1 3111.91   300.8 3110.58
   306.1 3112.76   314.2 3113.91   343.9 3111.69   357.7 3111.85     361 3112.88
   373.9  3122.4   395.3 3130.51   410.3 3140.06   415.9 3142.99   424.5 3145.14
#Mann= 3 ,-1,0
       0      .1       0   256.8    .045       0   271.3      .1       0
Bank Sta=256.8,271.3
XS Rating Curve= 0 ,0
Exp/Cntr(USF)=0,0
Exp/Cntr=0.3,0.1

Type RM Length L Ch R = 1 ,3514    ,174.2,173.9,173.9
XS GIS Cut Line= 2
2325212.34554137596820.8166724962325313.10232353597193.616766484
#Sta/Elev= 30
       0  3140.8    14.7 3136.09    41.8 3123.51    71.9 3110.97    83.2 3108.11
    91.5 3106.53     104 3105.99   108.1 3105.36   120.5 3105.96   128.8 3104.34
   137.2 3104.07     162 3106.09   179.6 3104.49   186.8  3104.3   207.6 3103.48
   210.8 3104.24   215.8 3106.47     220 3106.83   232.4 3105.04   236.6 3105.13
   257.3 3109.22   273.8 3110.32   311.1 3109.19   319.4 3110.26   331.9 3110.74
   348.4 3112.31   360.9 3115.17   369.1 3116.19   377.4 3118.77   386.2 3122.69
#Mann= 3 ,-1,0
       0      .1       0   186.8    .045       0   210.8      .1       0
#XS Ineff= 2 , 0
                           218.6         3111.52
Permanent Ineff=
       F       F
Bank Sta=186.8,210.8
XS Rating Curve= 0 ,0
Exp/Cntr(USF)=0,0
Exp/Cntr=0.3,0.1

Type RM Length L Ch R = 1 ,3340    ,168.8,170.8,172.8
XS GIS Cut Line= 2
 2325047.2453627596862.018140358 2325159.1397576597296.531907364
#Sta/Elev= 30
       0 3136.81     9.9 3131.98    19.8  3128.5      28 3124.34    36.3 3121.37
    42.8 3116.88    61.1 3102.05    65.2 3099.49    69.4 3098.13    81.7 3099.35
   102.4 3099.64   118.3 3101.83   156.1 3102.69   168.5 3102.71     185  3100.6
  208.49 3099.89   216.9 3098.69   222.2 3098.71   225.6 3099.84   234.6 3102.97
   246.4 3103.45   263.5 3102.77     299 3104.35     342 3102.62   370.9 3103.91
   391.5 3109.33   403.9  3113.8   416.3 3116.86   428.7 3122.87   448.7 3127.22
#Mann= 3 ,0,0
       0      .1       0  208.49    .045       0   225.6      .1       0
Bank Sta=208.49,225.6
XS Rating Curve= 0 ,0
Exp/Cntr(USF)=0,0
Exp/Cntr=0.3,0.1

Type RM Length L Ch R = 1 ,3169    ,332,328.3,324
XS GIS Cut Line= 3
  2324911.262975596909.4918331942324948.03417319597226.201834132
2325043.61705451597340.539924084
#Sta/Elev= 30
       0 3135.12    11.8 3127.15    35.9 3115.14      40 3112.01      52 3099.25
    56.1 3096.45    64.1 3094.18    76.2    3093    84.2 3095.14    88.3 3095.57
   136.6 3097.06   144.9 3096.75   152.7 3094.88   168.8 3094.86   177.73093.902
   184.9 3093.37   202.6 3093.92   217.1 3095.54   237.3 3094.57   249.4 3096.49
   261.4 3096.06   301.7 3097.07   333.1 3096.22   366.5 3096.09   400.6 3098.38
   411.3 3100.23   431.8  3106.3   447.8 3113.07   457.4 3118.27   467.9 3120.86
#Mann= 3 ,0,0
       0      .1       0   177.7    .045       0   202.6      .1       0
#XS Ineff= 2 , 0
                             251         3107.54
Permanent Ineff=
       F       F
Bank Sta=177.7,202.6
XS Rating Curve= 0 ,0
Exp/Cntr(USF)=0,0
Exp/Cntr=0.3,0.1

Type RM Length L Ch R = 1 ,2841    ,224.8,226.1,222.8
XS GIS Cut Line= 4
2324613.86757939596999.4721686142324611.59561199597124.430376119
2324666.69082166597274.3802251252324707.01824317597445.345772666
#Sta/Elev= 30
       0 3121.18    13.7 3117.15    21.7    3114    29.7 3111.92    53.7 3103.81
   113.4 3091.39   118.2 3090.15   125.8 3086.92     130 3086.55   138.6 3087.04
   142.8 3086.39   151.3 3083.28   172.8 3083.81   199.4 3083.27   206.7 3082.47
   212.8 3083.11   219.5  3083.5   228.1 3081.63   236.6 3082.43   245.1 3081.55
   274.9 3085.46   295.8 3086.06   308.2 3084.53   332.8 3088.17   349.3 3088.25
   365.7  3087.3   373.9 3087.41   406.8 3085.07   443.8 3085.95   460.4 3088.03
#Mann= 3 ,-1,0
       0      .1       0   199.4    .045       0   212.8      .1       0
#XS Ineff= 2 , 0
                          291.55         3090.24
Permanent Ineff=
       F       F
Bank Sta=199.4,212.8
XS Rating Curve= 0 ,0
Exp/Cntr(USF)=0,0
Exp/Cntr=0.3,0.1

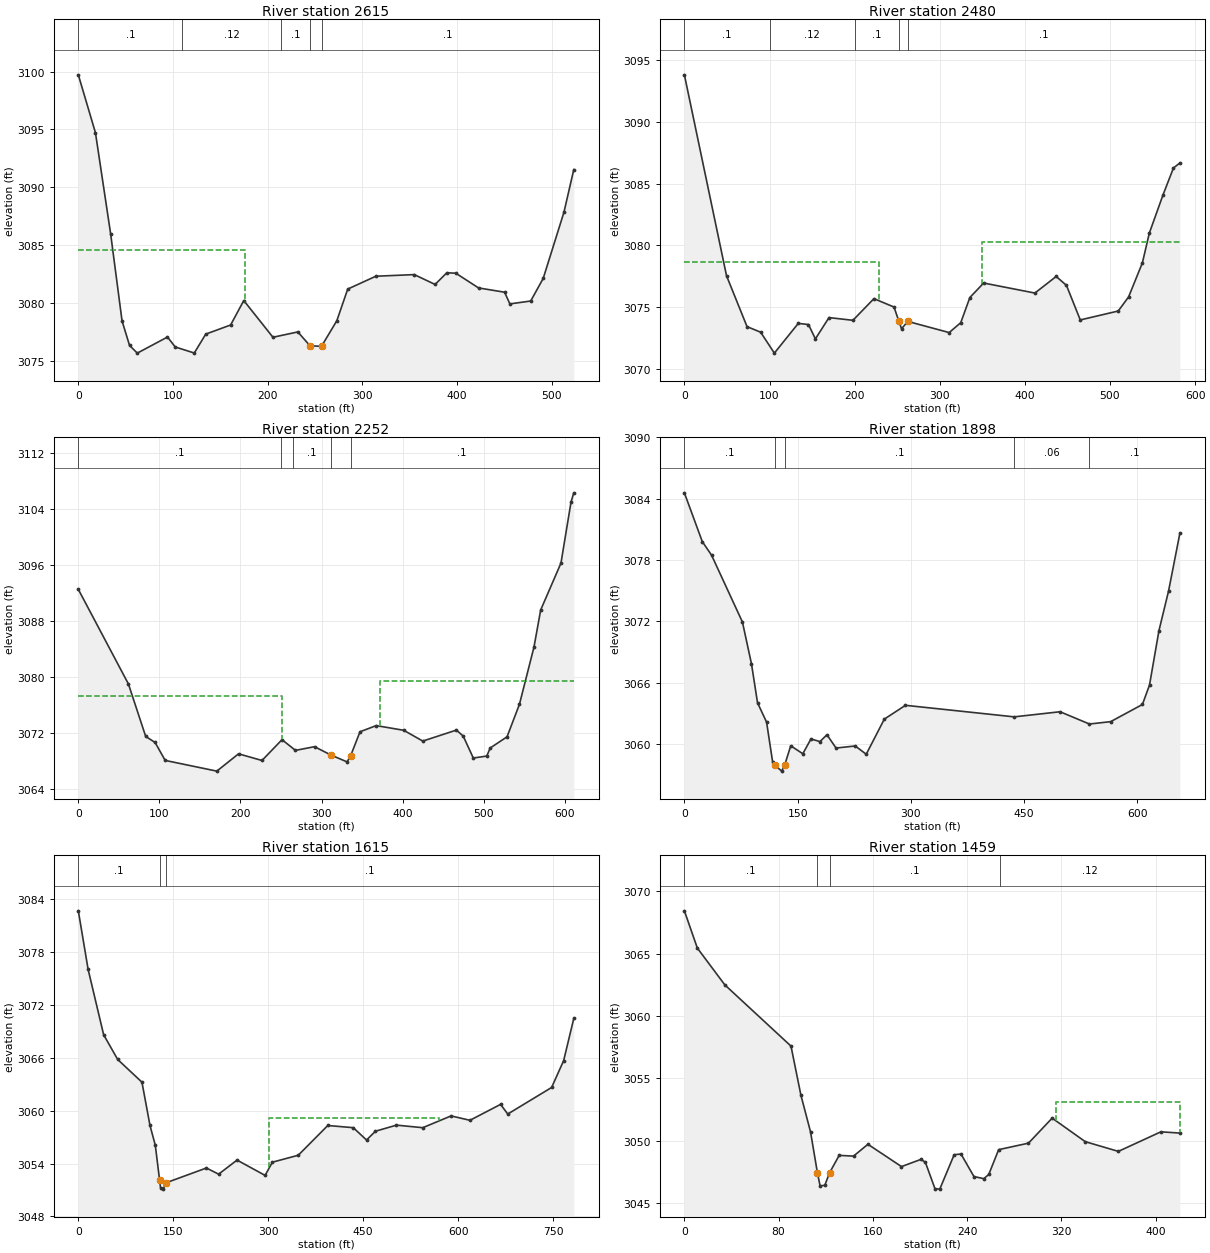
Type RM Length L Ch R = 1 ,2615    ,131.1,134.9,150.4
XS GIS Cut Line= 3
2324407.47982507597055.1529470422324423.14652441597228.207679403
2324567.52618973597546.594590332
#Sta/Elev= 30
       0 3099.72    18.1 3094.72    34.2 3085.96    46.2 3078.47    54.1 3076.36
    62.3 3075.69    94.2 3077.08   102.4 3076.22   122.5  3075.7   134.6 3077.33
   160.9 3078.12   174.8 3080.23   205.6 3077.06   231.9 3077.52   244.8 3076.32
   256.9 3076.28   273.1 3078.49   284.6 3081.22   314.3 3082.33   354.9 3082.47
   376.9 3081.62   389.3 3082.63   398.8 3082.59   422.8 3081.32   450.3 3080.95
   455.9 3079.94   477.9 3080.19   491.1 3082.14     513 3087.85   523.4 3091.54
#Mann= 5 ,-1,0
       0      .1       0     110     .12       0  213.76      .1       0
   244.8    .045       0   256.9      .1       0
#XS Ineff= 2 , 0
          176.45 3084.58
Permanent Ineff=
       F       F
Bank Sta=244.8,256.9
XS Rating Curve= 0 ,0
Exp/Cntr(USF)=0,0
Exp/Cntr=0.3,0.1

Type RM Length L Ch R = 1 ,2480    ,218.6,228,212.6
XS GIS Cut Line= 3
2324300.42976695  597063.8890748 2324321.1982477597303.860982519
2324376.38796282597640.593404464
#Sta/Elev= 30
       0 3093.78    49.5 3077.56    73.6 3073.45    89.6    3073   105.7 3071.31
   133.8 3073.71   145.8 3073.62   153.9 3072.46   169.9 3074.18     198 3073.96
   222.7 3075.71   246.3 3075.03     2523073.881   255.1 3073.28   262.5 3073.87
   311.1 3072.97   324.7 3073.77   335.4  3075.8   351.6 3076.97   411.8 3076.16
   436.8  3077.5   448.9 3076.78   465.1 3073.99   509.7 3074.71   521.9 3075.85
   538.1  3078.6   546.2 3080.99   562.4  3084.1   574.6 3086.26   582.1 3086.66
#Mann= 5 ,-1,0
       0      .1       0     100     .12       0     200      .1       0
     252    .045       0   262.5      .1       0
#XS Ineff= 2 , 0
          229.18 3078.64  349.18          3080.3
Permanent Ineff=
       F       F
Bank Sta=252,262.5
XS Rating Curve= 0 ,0
Exp/Cntr(USF)=0,0
Exp/Cntr=0.3,0.1

Type RM Length L Ch R = 1 ,2252    ,344.7,353.4,354.1
XS GIS Cut Line= 4
2324103.81089603597101.1427101752324163.93065558597348.302126513
2324171.50388027 597482.72686489 2324231.6090628597696.398171381
#Sta/Elev= 30
       0  3092.5    61.8 3078.99    83.1  3071.5    94.7 3070.64   107.1 3068.08
   170.8 3066.55   197.6 3069.02   226.5 3068.07   251.2 3071.04   267.8 3069.51
   291.3 3070.04   311.3 3068.86   331.4 3067.87   335.7 3068.71   347.4 3072.17
   367.4 3073.05   401.3 3072.38   424.8 3070.84   466.3 3072.41   474.7 3071.54
   487.1 3068.42   503.7  3068.7   507.9 3069.85   528.7 3071.45     544 3076.09
   561.9 3084.25   570.2 3089.56   595.2 3096.25   607.6 3104.96     611 3106.28
#Mann= 5 ,-1,0
       0      .1       0     250     .12       0  264.37      .1       0
   311.3    .045       0   335.7      .1       0
#XS Ineff= 2 , 0
          251.61 3077.34  372.28         3079.41
Permanent Ineff=
       F       F
Bank Sta=311.3,335.7
XS Rating Curve= 0 ,0
Exp/Cntr(USF)=0,0
Exp/Cntr=0.3,0.1

Type RM Length L Ch R = 1 ,1898    ,281.1,283.4,283.5
XS GIS Cut Line= 4
 2323897.3450997597117.9832828592323881.13888184597192.561869396
2323882.44225564597600.5640229672323971.89449203597747.510581256
#Sta/Elev= 30
       0 3084.58    23.7 3079.81      36 3078.48    76.9 3071.94    88.9 3067.84
    96.9 3064.04   108.9 3062.14   116.9 3058.26   119.83057.934   128.9 3057.35
   132.9 3057.95   140.9 3059.83   156.9 3059.05   167.7  3060.5   179.6 3060.24
   188.9 3060.91   200.9 3059.61   226.4 3059.81   240.9    3059   264.9 3062.44
   292.9 3063.79   436.9 3062.66   497.7 3063.16   536.6 3061.96   564.7 3062.19
   606.8 3063.87   616.2 3065.77   628.7 3071.09   641.5 3074.99   656.4 3080.61
#Mann= 5 ,-1,0
       0      .1       0   119.8    .045       0   132.9      .1       0
   436.9     .06       0   536.6      .1       0
Bank Sta=119.8,132.9
XS Rating Curve= 0 ,0
Exp/Cntr(USF)=0,0
Exp/Cntr=0.3,0.1

Type RM Length L Ch R = 1 ,1615    ,155.7,156.4,156.8
XS GIS Cut Line= 5
2323688.71325958597114.6161918292323647.66420018597229.055993787
2323619.66077245597453.833924701 2323718.0440652597597.447469594
2323937.71883693597737.220614284
#Sta/Elev= 30
       0 3082.71    15.5 3076.05      40 3068.63    62.2 3065.82   100.5 3063.24
   113.2 3058.32   121.6 3056.07   128.4 3052.09   129.8 3051.27   133.8 3051.09
   139.23051.827   202.3 3053.49   221.6 3052.79   250.7 3054.39     295 3052.65
   306.5 3054.15   347.4 3054.94     394 3058.32   434.3 3058.07   455.2 3056.67
   469.3 3057.67   502.5 3058.36     544 3058.07   588.7 3059.41   618.5 3058.91
   666.9 3060.72   678.2 3059.62   747.5 3062.64   766.5 3065.69   782.5 3070.48
#Mann= 3 ,-1,0
       0      .1       0   128.4    .045       0   139.2      .1       0
#XS Ineff= 1 ,-1
  301.38     5703059.218
Permanent Ineff=
       F
Bank Sta=128.4,139.2
XS Rating Curve= 0 ,0
Exp/Cntr(USF)=0,0
Exp/Cntr=0.3,0.1

Type RM Length L Ch R = 1 ,1459    ,150,144.4,140.2
XS GIS Cut Line= 5
2323536.05955193597102.3994739392323502.27431786597171.505634542
2323475.89168452597319.928348319 2323455.5440547597382.528763347
2323466.04642982597509.168731381
#Sta/Elev= 30
       0 3068.44      11 3065.45    34.3  3062.5    90.5 3057.58    98.9 3053.65
   107.1 3050.69   112.93047.429   115.2 3046.36   119.2 3046.41   123.3 3047.42
   131.4 3048.81   143.6 3048.75   155.8  3049.7   184.3 3047.91   200.9 3048.49
   204.6 3048.25   212.7 3046.14   216.8  3046.1     229 3048.86   234.8 3048.92
   245.8 3047.11   254.2 3046.94   258.4 3047.28   266.8 3049.27   292.1 3049.79
   312.2  3051.8   340.3 3049.91   368.4 3049.13   404.5  3050.7   420.6  3050.6
#Mann= 4 ,-1,0
       0      .1       0   112.9    .045       0   123.3      .1       0
  267.67     .12       0
#XS Ineff= 2 , 0
                          315.21         3053.07
Permanent Ineff=
       F       F
Bank Sta=112.9,123.3
XS Rating Curve= 0 ,0
Exp/Cntr(USF)=0,0
Exp/Cntr=0.3,0.1