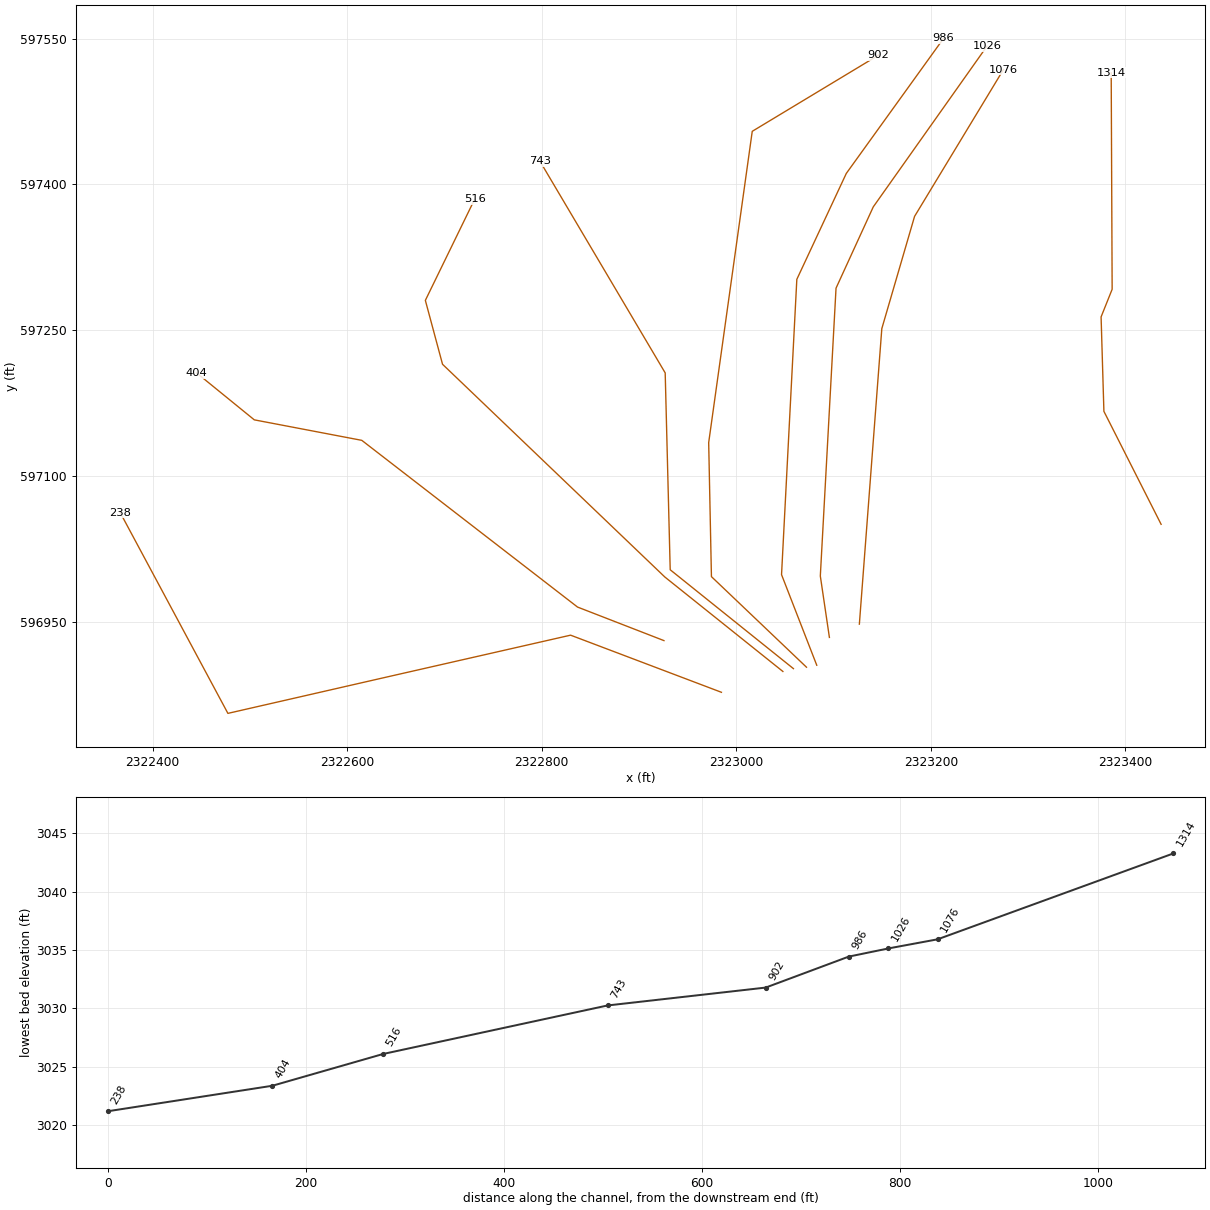
HEC-RAS study CLBHSERN.prj: CLBHSERN

--- CLBHSERN.g01 (geometry) --- (continued)

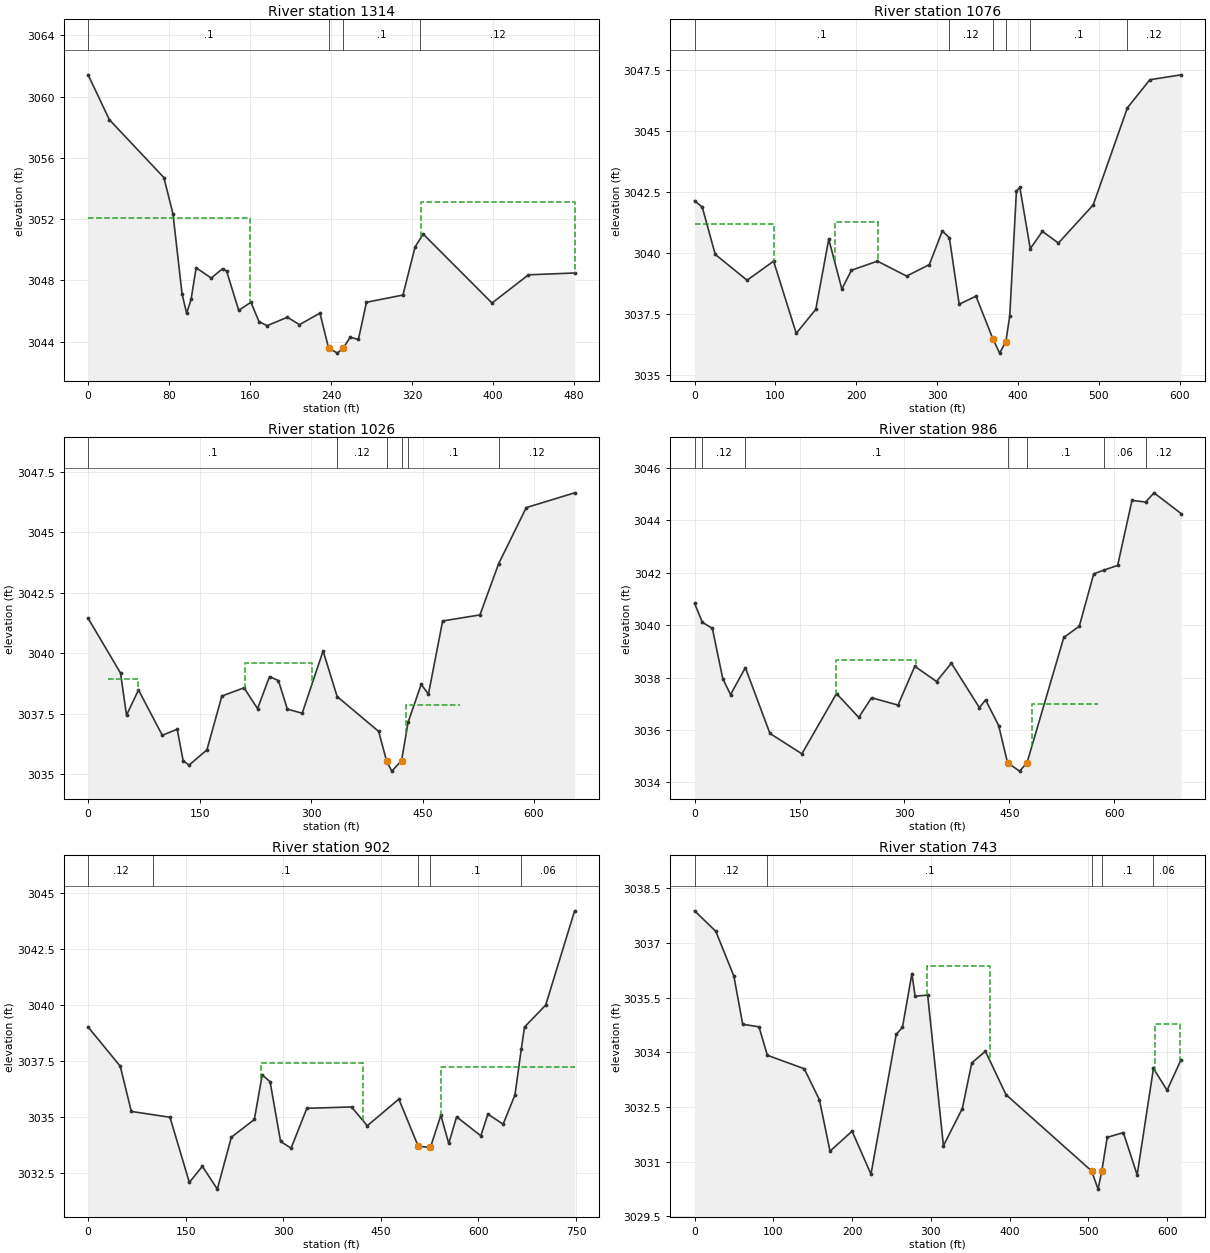
Type RM Length L Ch R = 1 ,1314    ,233.9,238.2,238.1
XS GIS Cut Line= 5
2323436.74991528597050.4085500412323377.94277466597166.604245773
2323375.05308294597263.7344507262323386.41291999597292.134043341
2323385.44671991597514.708925443
#Sta/Elev= 30
       0 3061.42      21 3058.49    74.8 3054.72    83.8 3052.36    92.8 3047.13
    97.3 3045.86   101.7 3046.76   106.7 3048.83   121.6 3048.16   132.8 3048.77
   136.8 3048.61   148.8 3046.05   160.8 3046.58   168.8 3045.32   176.8 3045.05
   196.8  3045.6   208.8 3045.12     229 3045.87   237.53043.601   246.2 3043.26
     252 3043.59     259  3044.3     267 3044.15     275 3046.58     311 3047.05
     323 3050.19     331 3051.03     399 3046.53     435 3048.37   480.6 3048.49
#Mann= 4 ,-1,0
       0      .1       0   237.5    .045       0     252      .1       0
  327.99     .12       0
#XS Ineff= 2 , 0
           160.3 3052.06   329.3         3053.13
Permanent Ineff=
       F       F
Bank Sta=237.5,252
XS Rating Curve= 0 ,0
Exp/Cntr(USF)=0,0
Exp/Cntr=0.3,0.1

Type RM Length L Ch R = 1 ,1076    ,52.1,49.6,47.8
BEGIN DESCRIPTION:
structure xs 4
END DESCRIPTION:
XS GIS Cut Line= 4
2323126.57453196596947.750329779 2323149.6601125597251.710473601
2323183.32658413597367.1383763182323274.70700711 597518.15654904
#Sta/Elev= 30
       0 3042.14     9.5 3041.88    25.5 3039.95    64.9 3038.89    97.7 3039.67
   125.7 3036.72   149.9  3037.7   165.9 3040.57   182.1 3038.53     194  3039.3
   226.1 3039.67   262.2 3039.06   290.3 3039.53   306.4 3040.91   315.1 3040.62
   327.2 3037.91     348 3038.24   368.73036.506   377.2 3035.91   384.93036.377
   389.7 3037.43     398 3042.54   402.2 3042.69   415.1 3040.18   430.1 3040.89
   449.9 3040.41   492.9 3041.97   535.2 3045.94     563 3047.09   601.6 3047.29
#Mann= 6 ,-1,0
       0      .1       0   315.1     .12       0   368.7    .045       0
   384.9     .12       0   415.1      .1       0   535.2     .12       0
#XS Ineff= 2 ,-1
       0    98.2 3041.19  173.13  226.37 3041.26
Permanent Ineff=
       F       F
Bank Sta=368.7,384.9
XS Rating Curve= 0 ,0
Exp/Cntr(USF)=0,0
Exp/Cntr=0.5,0.3

Type RM Length L Ch R = 1 ,1026    ,40.7,40.1,39.9
BEGIN DESCRIPTION:
structure xs 3
END DESCRIPTION:
XS GIS Cut Line= 5
2323095.77471036596934.0737362172323086.44246868596997.252885154
2323102.59374422597293.2898080262323140.88132144597376.917937218
2323257.75918875597542.159059959
#Sta/Elev= 30
       0 3041.44    43.6 3039.18    51.7 3037.44    67.8 3038.48    99.8 3036.61
   119.9 3036.86   127.9 3035.56   135.9 3035.38   159.9 3036.01     180 3038.23
   209.8 3038.57     228 3037.71   244.1 3039.03   256.1 3038.87   268.1 3037.69
   288.1 3037.52   316.2 3040.09   335.1 3038.21     391 3036.77  401.66 3035.55
   408.6 3035.13   421.8 3035.56   430.6 3037.15   448.2 3038.71     458 3038.31
   477.1 3041.33   527.3 3041.58   552.4 3043.69   589.6 3046.01   654.7 3046.62
#Mann= 6 ,-1,0
       0      .1       0   335.1     .12       0  401.66    .045       0
   421.8     .12       0   430.6      .1       0   552.4     .12       0
#XS Ineff= 4 ,-1
   26.82   67.04 3038.94  210.98   300.93039.596     314     387 3035.97
   427.8     500 3037.85
Permanent Ineff=
       F       F       F       F
Bank Sta=401.66,421.8
XS Rating Curve= 0 ,0
Exp/Cntr(USF)=0,0
Exp/Cntr=0.5,0.3

Type RM Length L Ch R = 1 ,986     ,79.4,83.9,89.4
BEGIN DESCRIPTION:
xs 2
END DESCRIPTION:
XS GIS Cut Line= 5
2323082.77434507 596905.465910892323046.57860814596998.627501035
2323062.29103136 597302.357918422323113.15003229597411.298166426
 2323213.1722975597550.238746321
#Sta/Elev= 30
       0 3040.83    11.1 3040.11    25.4 3039.88    40.3 3037.96    51.4 3037.35
    72.6 3038.38   107.7 3035.87   153.4 3035.09   202.9 3037.39   234.7 3036.48
     253 3037.23   290.8 3036.95   314.8 3038.43   345.9 3037.85   367.1 3038.55
   407.2 3036.85     416 3037.15   434.7 3036.17   447.4 3034.75   464.6 3034.43
  475.23 3034.75   527.8 3039.53     550 3039.96   570.6 3041.96   585.1  3042.1
   604.8 3042.28   625.3 3044.76   644.9  3044.7   656.8 3045.05   695.5 3044.26
#Mann= 7 ,-1,0
       0      .1       0    11.1     .12       0    72.6      .1       0
   447.4    .045       0  475.23      .1       0   585.1     .06       0
   644.9     .12       0
#XS Ineff= 3 ,-1
  201.92  315.89 3038.66  367.22     434    3035     482  577.39    3037
Permanent Ineff=
       F       F       F
Bank Sta=447.4,475.23
XS Rating Curve= 0 ,0
Exp/Cntr(USF)=0,0
Exp/Cntr=0.5,0.3

Type RM Length L Ch R = 1 ,902     ,153.4,159.7,170.6
XS GIS Cut Line= 5
2323072.23007915596903.4397411622322974.51554096596996.597454825
2322971.68650257597134.4242386042323016.46729464 597454.60690191
2323146.33159164597532.973288034
#Sta/Elev= 30
       0 3039.02    49.4 3037.27    66.4 3035.25   125.8 3034.99   155.6 3032.08
   175.6  3032.8   198.6 3031.78   220.2  3034.1   255.5 3034.89   267.6 3036.88
   279.7 3036.58   295.8 3033.91     312 3033.61   336.2 3035.39   404.9 3035.45
   429.1 3034.61   477.6  3035.8   507.43033.695   526.1 3033.64   542.2 3035.08
   554.3 3033.82   566.4 3035.01   603.6 3034.16   614.5 3035.13   637.9 3034.68
   656.1 3035.99   665.9 3038.05   670.8 3039.02   703.3    3040   747.8 3044.21
#Mann= 5 ,-1,0
       0     .12       0     100      .1       0   507.4    .045       0
   526.1      .1       0   665.9     .06       0
#XS Ineff= 2 ,-1
  266.37  423.143037.424  542.65   747.8 3037.22
Permanent Ineff=
       F       F
Bank Sta=507.4,526.1
XS Rating Curve= 0 ,0
Exp/Cntr(USF)=0,0
Exp/Cntr=0.3,0.1

Type RM Length L Ch R = 1 ,743     ,222.7,226.6,230.3
XS GIS Cut Line= 4
2323058.81200641596901.9642483942322932.13521718597003.660842122
2322926.98148759597206.1481448522322798.32962894597423.705782118
#Sta/Elev= 30
       0 3037.88    26.9 3037.32    49.9 3036.09    61.1 3034.77    81.8  3034.7
    92.4 3033.92   139.3 3033.55   158.5  3032.7     172 3031.29     200 3031.84
     224 3030.66     256 3034.49     264 3034.69     276 3036.16     280 3035.54
     296 3035.57     316 3031.44     340 3032.46     352 3033.71   369.3 3034.03
   395.5 3032.84   504.1 3030.75   512.4 3030.25   517.2 3030.76     524 3031.67
   544.5  3031.8     562 3030.64   582.7 3033.56     600 3032.96   617.8  3033.8
#Mann= 5 ,-1,0
       0     .12       0    92.4      .1       0   504.1    .045       0
   517.2      .1       0   582.7     .06       0
#XS Ineff= 2 ,-1
   294.7  375.443036.376  585.24  616.39 3034.78
Permanent Ineff=
       F       F
Bank Sta=504.1,517.2
XS Rating Curve= 0 ,0
Exp/Cntr(USF)=0,0
Exp/Cntr=0.3,0.1

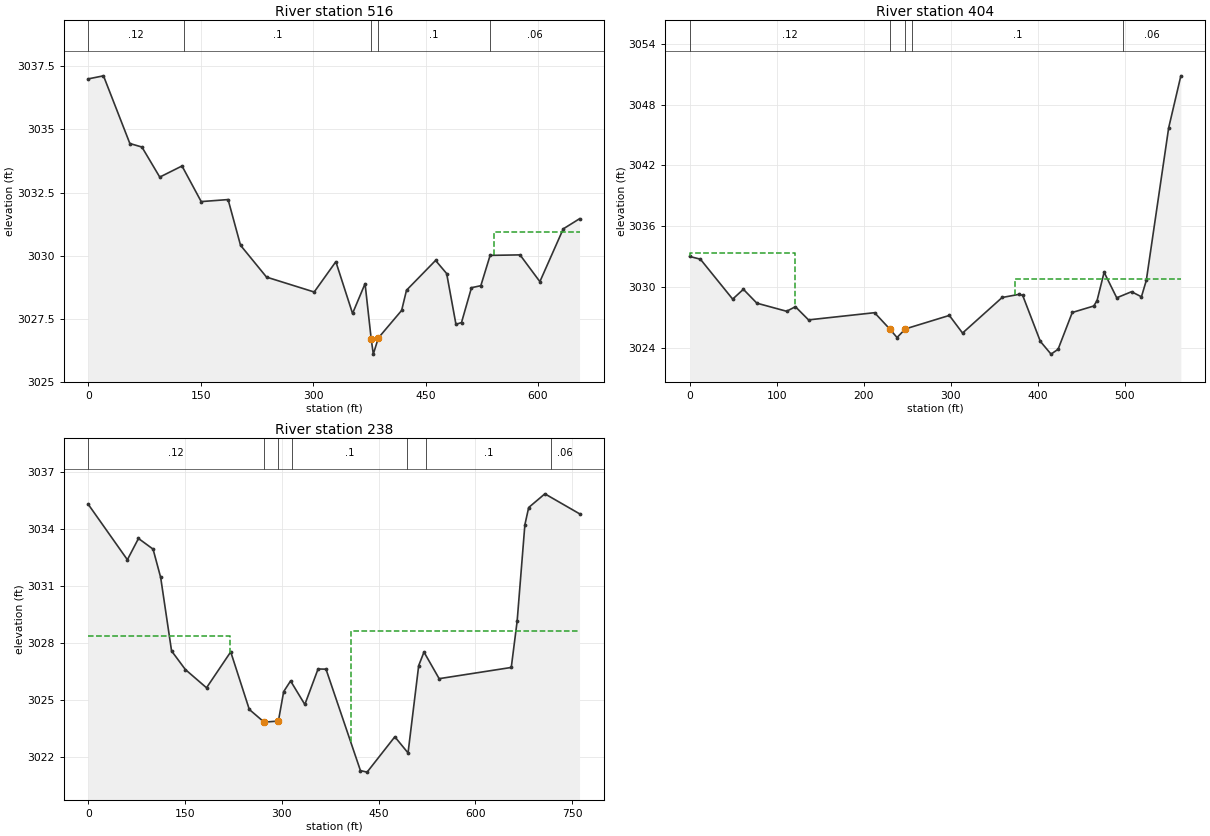
Type RM Length L Ch R = 1 ,516     ,112.9,111.9,112
XS GIS Cut Line= 5
2323047.96047253596899.0698411142322926.60853229596996.225115378
2322698.10541011597215.0155768852322680.44510597597280.731750906
2322731.08700128597384.690786447
#Sta/Elev= 30
       0    3037    20.2 3037.12    55.4 3034.44    71.5  3034.3    95.3 3033.11
     125 3033.55   150.6 3032.14   186.5 3032.22   203.1 3030.41   237.8 3029.15
   301.4 3028.56   330.3 3029.76   352.6 3027.71   369.3 3028.89   377.53026.696
   380.3  3026.1     387 3026.74   418.1 3027.83   424.6 3028.63   463.4 3029.81
   478.2 3029.29   490.6 3027.28     498 3027.35   511.3 3028.73   523.8 3028.81
   536.2 3030.01   576.1 3030.03   602.6 3028.97   633.8 3031.06   655.5 3031.46
#Mann= 5 ,-1,0
       0     .12       0  127.06      .1       0   377.5    .045       0
     387      .1       0   536.2     .06       0
#XS Ineff= 2 , 0
                          541.57         3030.93
Permanent Ineff=
       F       F
Bank Sta=377.5,387
XS Rating Curve= 0 ,0
Exp/Cntr(USF)=0,0
Exp/Cntr=0.3,0.1

Type RM Length L Ch R = 1 ,404     ,142.8,166.1,182
XS GIS Cut Line= 5
2322925.71137513596930.8000711262322836.86783006596965.308687517
2322615.10633269597136.7711723492322504.61222624597157.853095964
2322445.34758814597206.095907711
#Sta/Elev= 30
       0 3033.02    12.3 3032.75    49.4 3028.81    61.7 3029.78    77.2 3028.41
   111.4 3027.61   121.5 3028.06   136.6 3026.76   212.5 3027.47   229.7 3025.88
   238.3 3025.02   247.9 3025.87   298.4  3027.2   313.6 3025.46   359.1 3028.97
   378.5 3029.28   382.7 3029.18     403 3024.64   415.3 3023.38   423.4 3023.86
   439.7 3027.49   464.4 3028.13   468.2 3028.67   476.3 3031.46   490.8 3028.94
   507.8 3029.54   519.2 3029.04   524.8 3030.66   550.5 3045.72   564.5 3050.85
#Mann= 5 ,-1,0
       0     .12       0   229.7    .045       0   247.9     .12       0
  255.31      .1       0  498.11     .06       0
#XS Ineff= 2 , 0
           120.6 3033.35  373.75         3030.82
Permanent Ineff=
       F       F
Bank Sta=229.7,247.9
XS Rating Curve= 0 ,0
Exp/Cntr(USF)=0,0
Exp/Cntr=0.3,0.1

Type RM Length L Ch R = 1 ,238     ,,,
XS GIS Cut Line= 5
2322984.78773309596877.643765352 2322829.7401337596936.398645121
2322636.33865446596892.3324852952322477.48448532596855.959563993
2322366.78861623597062.426016466
#Sta/Elev= 30
       0 3035.29    60.5 3032.38    77.7  3033.5   100.3 3032.94   112.1 3031.45
     129 3027.58   150.4  3026.6   183.2 3025.64   220.7 3027.53   249.5  3024.5
  272.52 3023.83   294.6 3023.89   302.8 3025.44   313.5    3026   335.6 3024.76
   356.1 3026.63   368.4 3026.62   421.8 3021.28   432.1  3021.2   475.1 3023.06
   495.6 3022.21   512.1 3026.81   520.3 3027.52   543.8 3026.12   655.6 3026.71
   664.7 3029.14   676.7 3034.22   682.6 3035.13   707.7 3035.85   761.4  3034.8
#Mann= 7 ,-1,0
       0     .12       0  272.52    .045       0   294.6     .12       0
  315.81      .1       0  494.16     .12       0  524.16      .1       0
  717.13     .06       0
#XS Ineff= 2 , 0
          219.27 3028.38  406.64         3028.61
Permanent Ineff=
       F       F
Bank Sta=272.52,294.6
XS Rating Curve= 0 ,0
Exp/Cntr(USF)=0,0
Exp/Cntr=0.3,0.1
LCMann Table=0

Chan Stop Cuts=-1
Use User Specified Reach Order=0
Composite Channel Slope=5